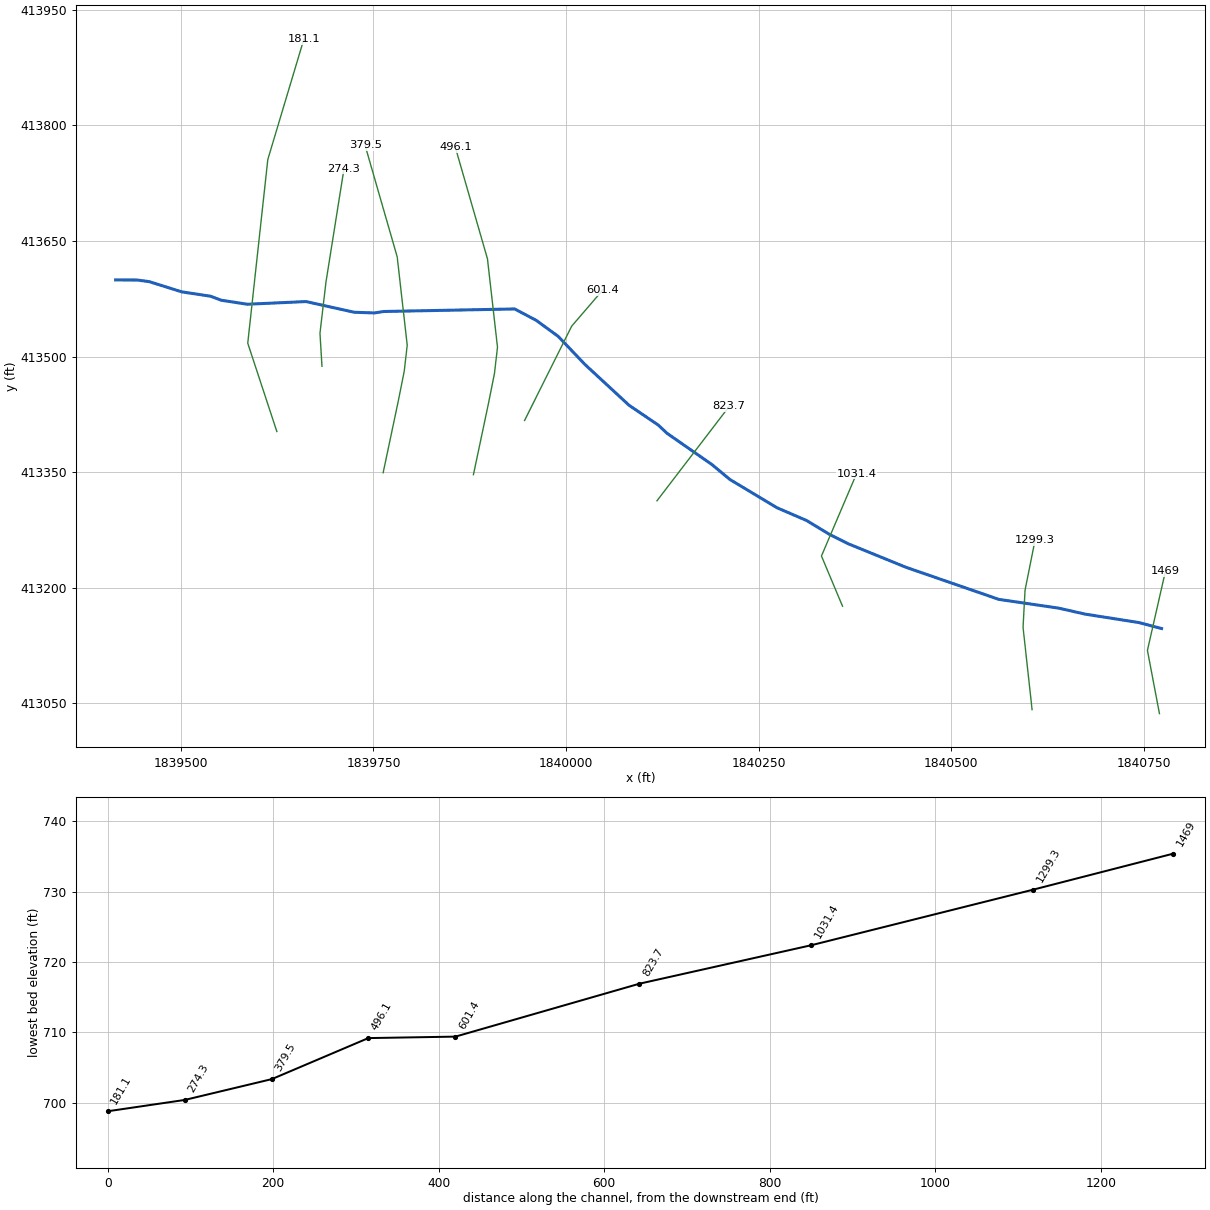
--- GREENSBRCH.prj (project) ---

Proj Title=GREENSBRCH
Current Plan=p01
Default Exp/Contr=0,0
English Units
Geom File=g01
Flow File=f01
Plan File=p01
BEGIN DESCRIPTION:
END DESCRIPTION:
DSS Export Rating Curves= 0
DSS Export Rating Curve Sorted= 0
DSS Export Volume Flow Curves= 0
DXF OffsetX= 0
DXF OffsetY= 0
DXF ScaleX= 0
DXF ScaleY= 0

--- GREENSBRCH.p01 (plan) ---

Plan Title=Floodplain
Program Version=4.00
Geom File=g01
Flow File=f01
K Sum by GR=0
Std Step Tol=0.01
Critical Tol=0.01
Num of Std Step Trials=20
Max Error Tol=0.3
Flow Tol Ratio=0.001
Split Flow NTrial=30
Split Flow Tol=0.02
Split Flow Ratio=0.02
Log Output Level=0
Friction Slope Method=1
Unsteady Friction Slope Method=2
Unsteady Bridges Friction Slope Method=1
Global Log Level=0
CheckData=False
Run HTab=0
Run UNet=0
Run PostProcess=0
UNET Theta=0
UNET Theta Warmup=0
UNET ZTol=0
UNET ZSATol=0
UNET MxIter=0
UNET MaxInSteps=0
UNET DtIC=0
UNET DtMin=0
UNET MaxCRTS=0
UNET WFStab=0
UNET SFStab=0
UNET WFX=0
UNET SFX=0
UNET DSS MLevel=0
UNET DZMax Abort=0
UNET Convert EG Bridges=0
UNET Use Existing IB Tables=0
UNET Froude Limit=0
UNET Froude Power=0
Write IC File=0
Echo Input=False
Echo Output=False
Write Detailed=0

--- GREENSBRCH.f01 (steady flow) ---

Flow Title=NFF Regression Equation
Program Version=4.00
Number of Profiles=1
Profile Names=P100yr
River Rch & RM=GREENSBRCH,Main      ,1469
699.9699
River Rch & RM=GREENSBRCH,Main      ,1299.3
939.7545
Boundary for River Rch & Prof#=GREENSBRCH,Main      ,1
Up Type=0
Dn Type=3
Dn Slope=0.031817

--- GREENSBRCH.g01 (geometry) ---

Geom Title=USGS 10m DEM
Program Version=4.10

River Reach=GREENSBRCH      ,Main
Reach XY= 30
     1840773.175       413147.23     1840743.728      413154.954
     1840673.899      413165.922     1840639.177      413173.734
      1840561.92      413185.019      1840441.26      413226.686
     1840366.607      413257.068     1840342.302       413269.22
     1840312.268      413287.344      1840273.69      413303.973
     1840212.926      413340.431      1840189.52       413359.84
     1840131.364      413400.297     1840119.468      413411.343
      1840081.85      413436.785     1840024.558      413489.736
     1839989.836      413526.195      1839961.19      413547.028
       1839933.3      413561.716     1839763.624      413558.417
     1839751.156      413556.547     1839725.114      413557.415
     1839662.614      413571.304     1839586.226      413567.831
     1839552.371       413573.04     1839538.482      413578.248
     1839501.156       413583.89     1839458.871      413597.145
     1839443.269       413599.25     1839415.279      413599.349

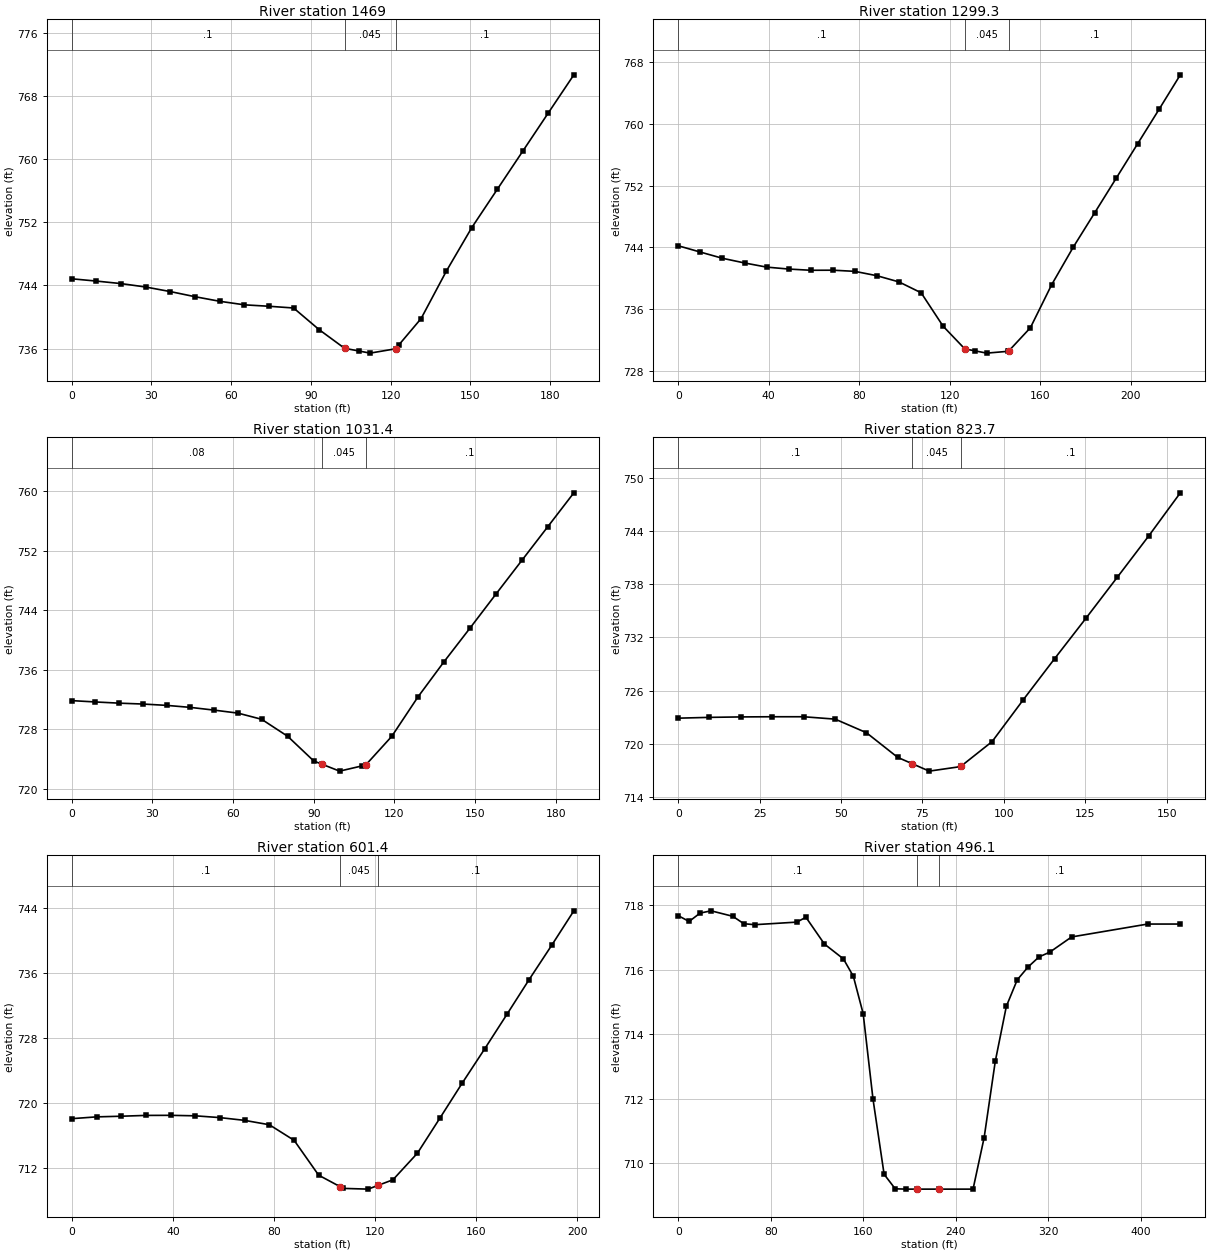
Type RM Length L Ch R = 1 ,1469    ,165.6,169.7,172.6
XS GIS Cut Line= 3
     1840770.427      413036.842     1840754.802      413118.873
     1840778.239      413221.738
#Sta/Elev= 23
       0  744.84     9.3  744.55    18.6  744.23    27.8   743.8    37.1  743.22
    46.4  742.57    55.7  741.99      65  741.54    74.2  741.36    83.5  741.14
    93.1   738.4   102.7  736.03   108.1  735.69   112.3  735.42   121.9  735.97
   123.1  736.45   131.5   739.8     141  745.81   150.6  751.34   160.2  756.19
   169.8  761.03   179.4  765.87     189  770.69
#Mann= 3 , 0 , 0
       0      .1       0   102.7    .045       0   121.9      .1       0
Bank Sta=102.7,121.9
XS Rating Curve= 0 ,0
Exp/Cntr=0.3,0.1

Type RM Length L Ch R = 1 ,1299.3  ,275.8,267.9,260.8
XS GIS Cut Line= 4
     1840605.062       413042.05     1840593.344      413148.821
     1840595.948      413196.998     1840608.969      413262.102
#Sta/Elev= 26
       0  744.22     9.8   743.4    19.5   742.6    29.3  741.99    39.1  741.45
    48.8   741.2    58.6  741.04    68.4  741.05    78.1   740.9    87.9  740.33
    97.6  739.53   107.4  738.12   117.1  733.79   126.7  730.84   131.3  730.58
   136.4  730.29     146  730.53   146.3  730.62   155.7  733.58   165.1  739.16
   174.6  744.01   184.1  748.48   193.6  752.96   203.1  757.44   212.6  761.92
     222   766.4
#Mann= 3 , 0 , 0
       0      .1       0   126.7    .045       0   146.3      .1       0
Bank Sta=126.7,146.3
XS Rating Curve= 0 ,0
Exp/Cntr=0.3,0.1

Type RM Length L Ch R = 1 ,1031.4  ,213.1,207.7,201.8
XS GIS Cut Line= 3
     1840358.969      413176.165     1840331.625      413241.269
     1840377.198       413348.04
#Sta/Elev= 23
       0  731.88     8.8   731.7    17.6  731.54    26.5  731.42    35.3  731.24
    44.1  730.97      53   730.6    61.8   730.2    70.6  729.37    80.3  727.08
      90  723.76    92.9  723.35    99.6   722.4   107.9   723.1   109.3  723.22
     119  727.08   128.7  732.36   138.3  737.05     148  741.59   157.7  746.19
   167.4  750.75     177  755.26   186.7  759.82
#Mann= 3 , 0 , 0
       0     .08       0    92.9    .045       0   109.3      .1       0
Bank Sta=92.9,109.3
XS Rating Curve= 0 ,0
Exp/Cntr=0.3,0.1

Type RM Length L Ch R = 1 ,823.7   ,217.7,222.3,226.5
XS GIS Cut Line= 2
     1840118.083      413312.883     1840211.833      413435.279
#Sta/Elev= 19
       0   722.9     9.6  722.99    19.3  723.04    28.9  723.06    38.5  723.06
    48.2  722.79    57.8  721.26    67.4  718.48    71.9  717.76    77.1  716.93
    86.7  717.44    86.9   717.5    96.4  720.26     106  724.99   115.6  729.61
   125.3   734.2   134.9  738.81   144.5  743.44   154.2   748.3
#Mann= 3 , 0 , 0
       0      .1       0    71.9    .045       0    86.9      .1       0
Bank Sta=71.9,86.9
XS Rating Curve= 0 ,0
Exp/Cntr=0.3,0.1

Type RM Length L Ch R = 1 ,601.4   ,92,105.3,118.1
XS GIS Cut Line= 3
     1839946.208       413417.05     1840007.406      413539.446
     1840047.771      413586.321
#Sta/Elev= 24
       0  718.09     9.8  718.31    19.6  718.39    29.3  718.49    39.1   718.5
    48.9  718.44    58.6  718.22    68.4  717.88    78.2  717.34      88  715.42
    97.7  711.13   106.1  709.73   107.5   709.5   117.3  709.41   121.1  709.86
   127.1  710.56   136.8  713.84   145.7  718.16   154.5  722.46   163.4  726.68
   172.2  730.93     181  735.22   189.9  739.43   198.7  743.69
#Mann= 3 , 0 , 0
       0      .1       0   106.1    .045       0   121.1      .1       0
Bank Sta=106.1,121.1
XS Rating Curve= 0 ,0
Exp/Cntr=0.3,0.1

Type RM Length L Ch R = 1 ,496.1   ,116.6,116.6,116.6
XS GIS Cut Line= 6
     1839879.802      413346.738     1839899.333      413439.186
     1839907.146      413478.248     1839911.052      413512.102
     1839898.031      413626.686     1839856.364      413771.217
#Sta/Elev= 30
       0  717.68     9.4   717.5    18.9  717.76    28.4  717.83    47.2  717.66
    56.7  717.43    66.1   717.4   102.5  717.48   110.4  717.63   126.4   716.8
   142.8  716.34   151.4   715.8   159.9  714.64   168.4  711.99     178  709.66
   187.6  709.21   197.2   709.2   206.8   709.2   225.7   709.2   254.9   709.2
   264.5   710.8   274.1  713.16   283.7  714.87   293.1  715.69   302.5  716.09
   311.9   716.4   321.3  716.55   340.1  717.02   405.9  717.42   434.1  717.42
#Mann= 3 , 0 , 0
       0      .1       0   206.8    .045       0   225.7      .1       0
Bank Sta=206.8,225.7
XS Rating Curve= 0 ,0
Exp/Cntr=0.3,0.1

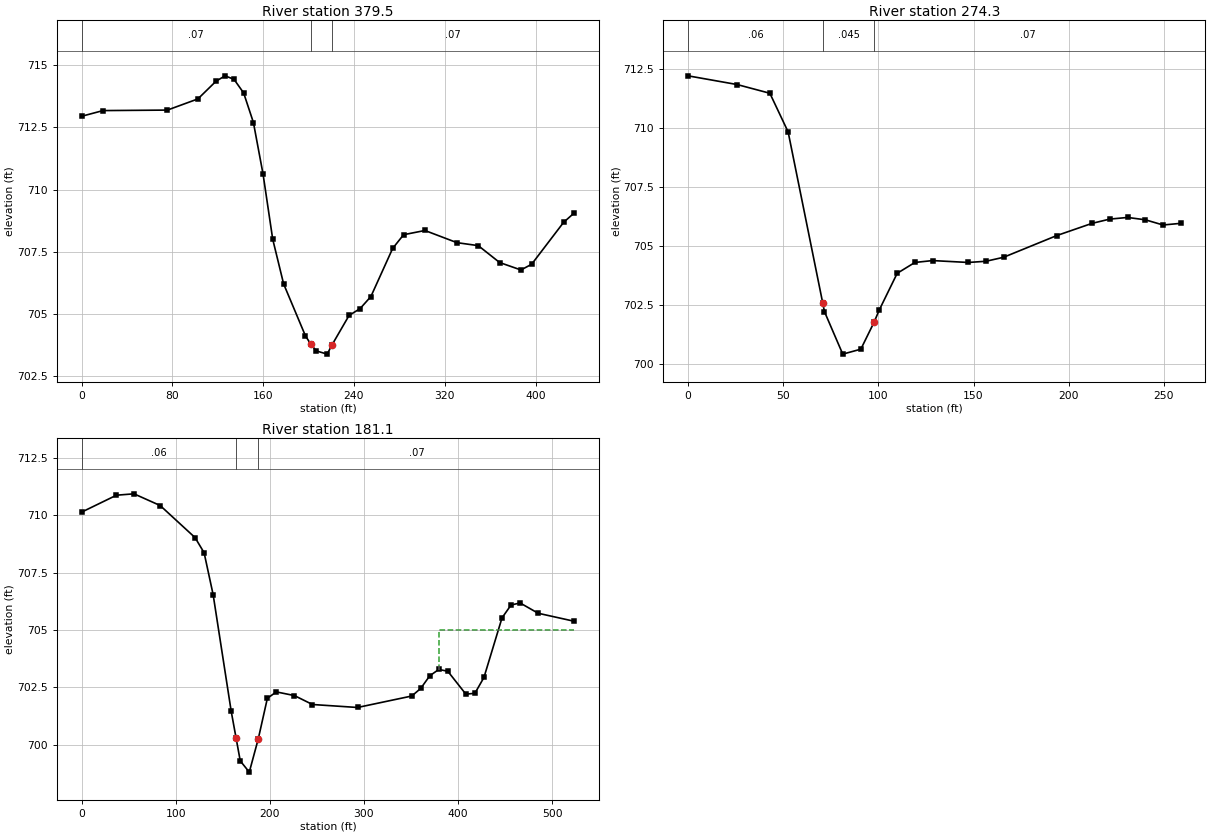
Type RM Length L Ch R = 1 ,379.5   ,110.2,105.2,99.8
XS GIS Cut Line= 6
     1839762.614      413349.342     1839782.146       413441.79
     1839789.958      413480.852     1839793.864      413514.706
     1839780.844       413629.29     1839739.177      413773.821
#Sta/Elev= 30
       0  712.95    18.9  713.18    75.6   713.2   102.5  713.65   118.4  714.36
   126.4  714.58   134.3  714.44   142.8  713.89   151.4   712.7   159.9  710.62
   168.4     708     178   706.2   197.2  704.11  201.95  703.77   206.8   703.5
   216.4  703.37   220.5  703.73   235.7  704.93   245.3   705.2   254.9  705.69
   274.1  707.63   283.7  708.18   302.5  708.35   330.7  707.86   349.5  707.74
   368.3  707.06   387.1  706.76   396.5  706.99   424.7  708.68   434.1  709.06
#Mann= 3 , 0 , 0
       0     .07       0  201.95    .045       0   220.5     .07       0
Bank Sta=201.95,220.5
XS Rating Curve= 0 ,0
Exp/Cntr=0.3,0.1

Type RM Length L Ch R = 1 ,274.3   ,92.9,93.2,93.2
XS GIS Cut Line= 4
     1839683.187      413487.363     1839680.583      413530.331
     1839688.396      413596.738     1839711.833      413743.873
#Sta/Elev= 23
       0  712.22    25.8  711.85      43  711.48    52.6  709.84    70.8  702.57
    71.7  702.21    81.3  700.41    90.8  700.62   97.79  701.77   100.4  702.27
   109.9  703.84   119.2   704.3   128.5  704.38   147.2   704.3   156.5  704.35
   165.8  704.52   193.7  705.44   212.3  705.96   221.6  706.14     231  706.21
   240.3  706.11   249.6  705.89   258.9  705.96
#Mann= 3 , 0 , 0
       0     .06       0    70.8    .045       0   97.79     .07       0
Bank Sta=70.8,97.79
XS Rating Curve= 0 ,0
Exp/Cntr=0.3,0.1

Type RM Length L Ch R = 1 ,181.1   ,179.4,181.1,182.1
XS GIS Cut Line= 4
     1839624.594      413402.727     1839586.833      413517.311
     1839612.875      413755.592      1839659.75      413911.842
#Sta/Elev= 30
       0  710.14    37.1  710.88    55.7  710.94    83.5  710.43   120.6  709.03
   130.2  708.37   139.8  706.54     159  701.45   164.2  700.28   168.6  699.29
   178.2   698.8   187.8  700.26   197.4  702.02   206.9   702.3   226.1  702.14
   245.3  701.75   293.2  701.62   350.8  702.12   360.3  702.45   369.9     703
   379.5  703.28   389.1   703.2   408.3   702.2   417.9  702.24   427.5  702.93
   446.7  705.53   456.3  706.09   465.9  706.18   485.1  705.73   523.5  705.38
#Mann= 3 , 0 , 0
       0     .06       0   164.2    .045       0   187.8     .07       0
#XS Ineff= 2 , 0
                          379.98          704.98
Permanent Ineff=
       F       F
Bank Sta=164.2,187.8
XS Rating Curve= 0 ,0
Exp/Cntr=0.3,0.1

Chan Stop Cuts=-1
Use User Specified Reach Order=0
Composite Channel Slope=5